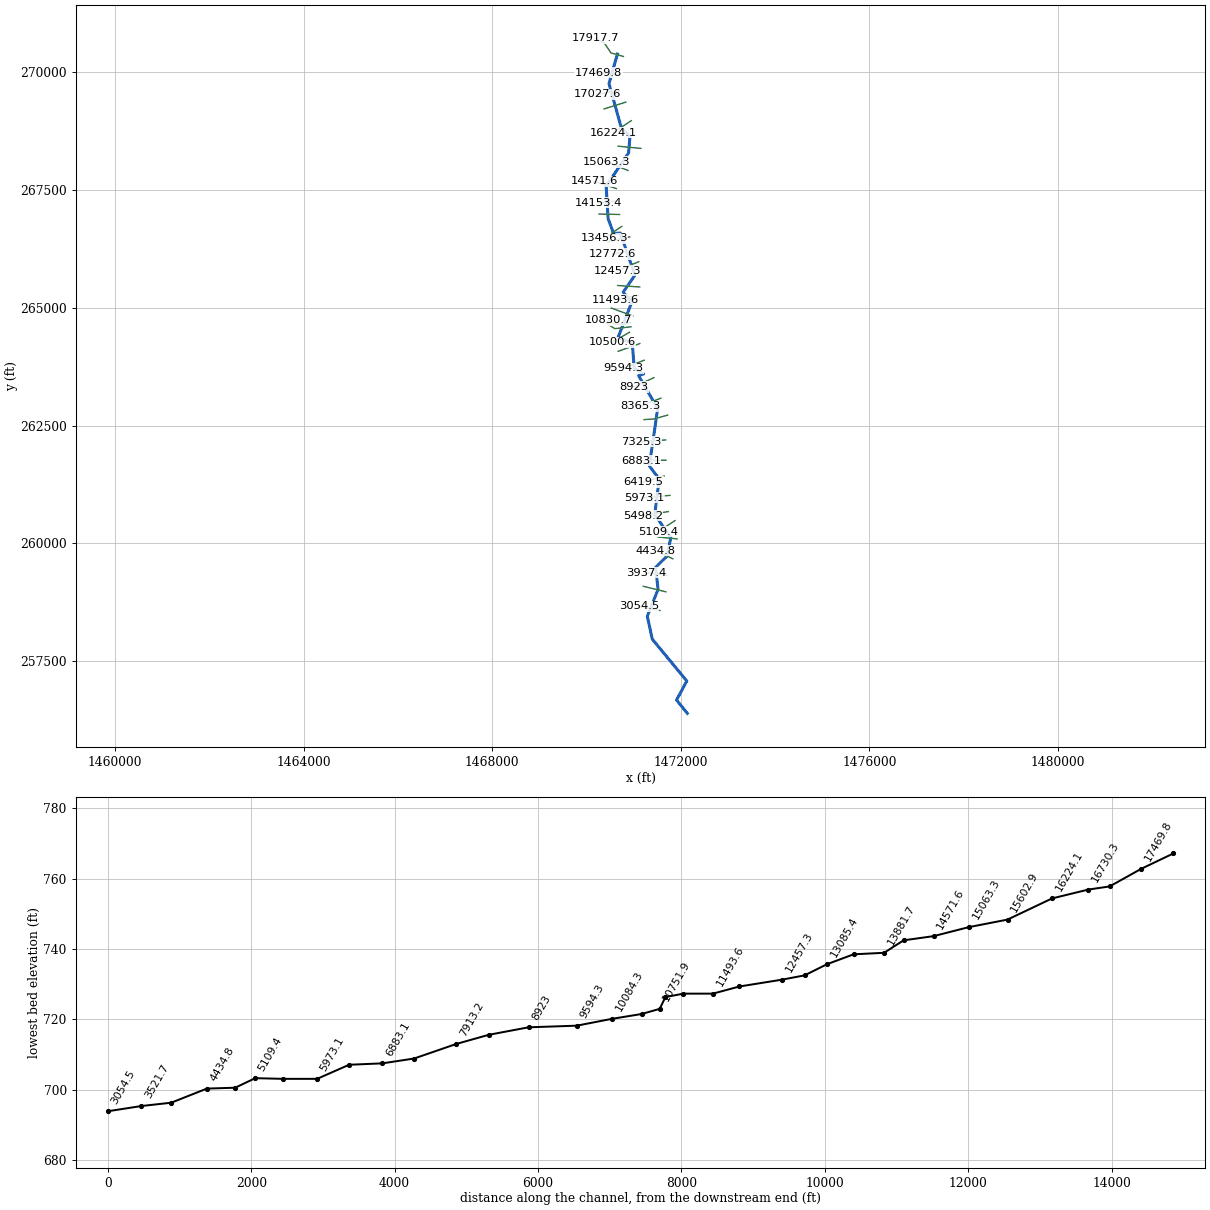
--- MYRSFR.prj (project) ---

Proj Title=MYRSFR
Current Plan=p01
Default Exp/Contr=0,0
English Units
Geom File=g01
Flow File=f01
Plan File=p01
BEGIN DESCRIPTION:
END DESCRIPTION:
DSS Export Rating Curves= 0
DSS Export Rating Curve Sorted= 0
DSS Export Volume Flow Curves= 0
DXF OffsetX= 0
DXF OffsetY= 0
DXF ScaleX= 0
DXF ScaleY= 0

--- MYRSFR.p01 (plan) ---

Plan Title=Floodplain
Program Version=4.00
Geom File=g01
Flow File=f01
K Sum by GR=0
Std Step Tol=0.01
Critical Tol=0.01
Num of Std Step Trials=20
Max Error Tol=0.3
Flow Tol Ratio=0.001
Split Flow NTrial=30
Split Flow Tol=0.02
Split Flow Ratio=0.02
Log Output Level=0
Friction Slope Method=1
Unsteady Friction Slope Method=2
Unsteady Bridges Friction Slope Method=1
Global Log Level=0
CheckData=False
Run HTab=0
Run UNet=0
Run PostProcess=0
UNET Theta=0
UNET Theta Warmup=0
UNET ZTol=0
UNET ZSATol=0
UNET MxIter=0
UNET MaxInSteps=0
UNET DtIC=0
UNET DtMin=0
UNET MaxCRTS=0
UNET WFStab=0
UNET SFStab=0
UNET WFX=0
UNET SFX=0
UNET DSS MLevel=0
UNET DZMax Abort=0
UNET Convert EG Bridges=0
UNET Use Existing IB Tables=0
UNET Froude Limit=0
UNET Froude Power=0
Write IC File=0
Echo Input=False
Echo Output=False
Write Detailed=0

--- MYRSFR.f01 (steady flow) ---

Flow Title=NFF Regression Equation
Program Version=4.10
Number of Profiles= 1
Profile Names=P100yr
River Rch & RM=MYRSFR,Main            ,17917.7
985.2362
River Rch & RM=MYRSFR,Main            ,17027.6
1038.632
River Rch & RM=MYRSFR,Main            ,15063.3
1097.768
River Rch & RM=MYRSFR,Main            ,14153.4
1213.501
River Rch & RM=MYRSFR,Main            ,11082.8
1300.685
River Rch & RM=MYRSFR,Main            ,7325.3
1445.144
River Rch & RM=MYRSFR,Main            ,849.4
1587.801
River Rch & RM=MYRSFR,Main            ,567.1
1589.203
Boundary for River Rch & Prof#=MYRSFR,Main            , 1
Up Type= 0
Dn Type= 3
Dn Slope=0.0055
DSS Import GetInterval= 0
DSS Import GetPeak= 0
DSS Import FillOption= 0

--- MYRSFR.g01 (geometry) ---

Geom Title=USGS 10m DEM
Program Version=4.10

River Reach=MYRSFR          ,Main
Reach XY= 30
     1470655.189      270379.428      1470476.59      269752.485
     1470738.953      268809.383     1470921.508      268637.505
     1470891.853       268282.11     1470416.065      267577.576
     1470457.781      266888.688      1470574.26      266574.444
     1470716.645      266583.465     1471027.208       265690.54
      1470777.47        265328.7     1470958.486      265115.631
     1470670.145      264371.457     1470970.924      264242.765
     1471011.676      263714.816     1471210.494      263595.142
     1471105.391      263555.669     1471508.982       262859.47
     1471331.452      261644.294     1471542.129      261366.955
     1471445.861      260614.871     1471787.078      260120.997
     1471703.336      259728.062     1471466.174      259494.276
      1471516.81      259024.758     1471288.656      258455.897
     1471394.407      257970.223     1472126.598      257082.886
     1471909.438      256679.299     1472138.395      256396.181

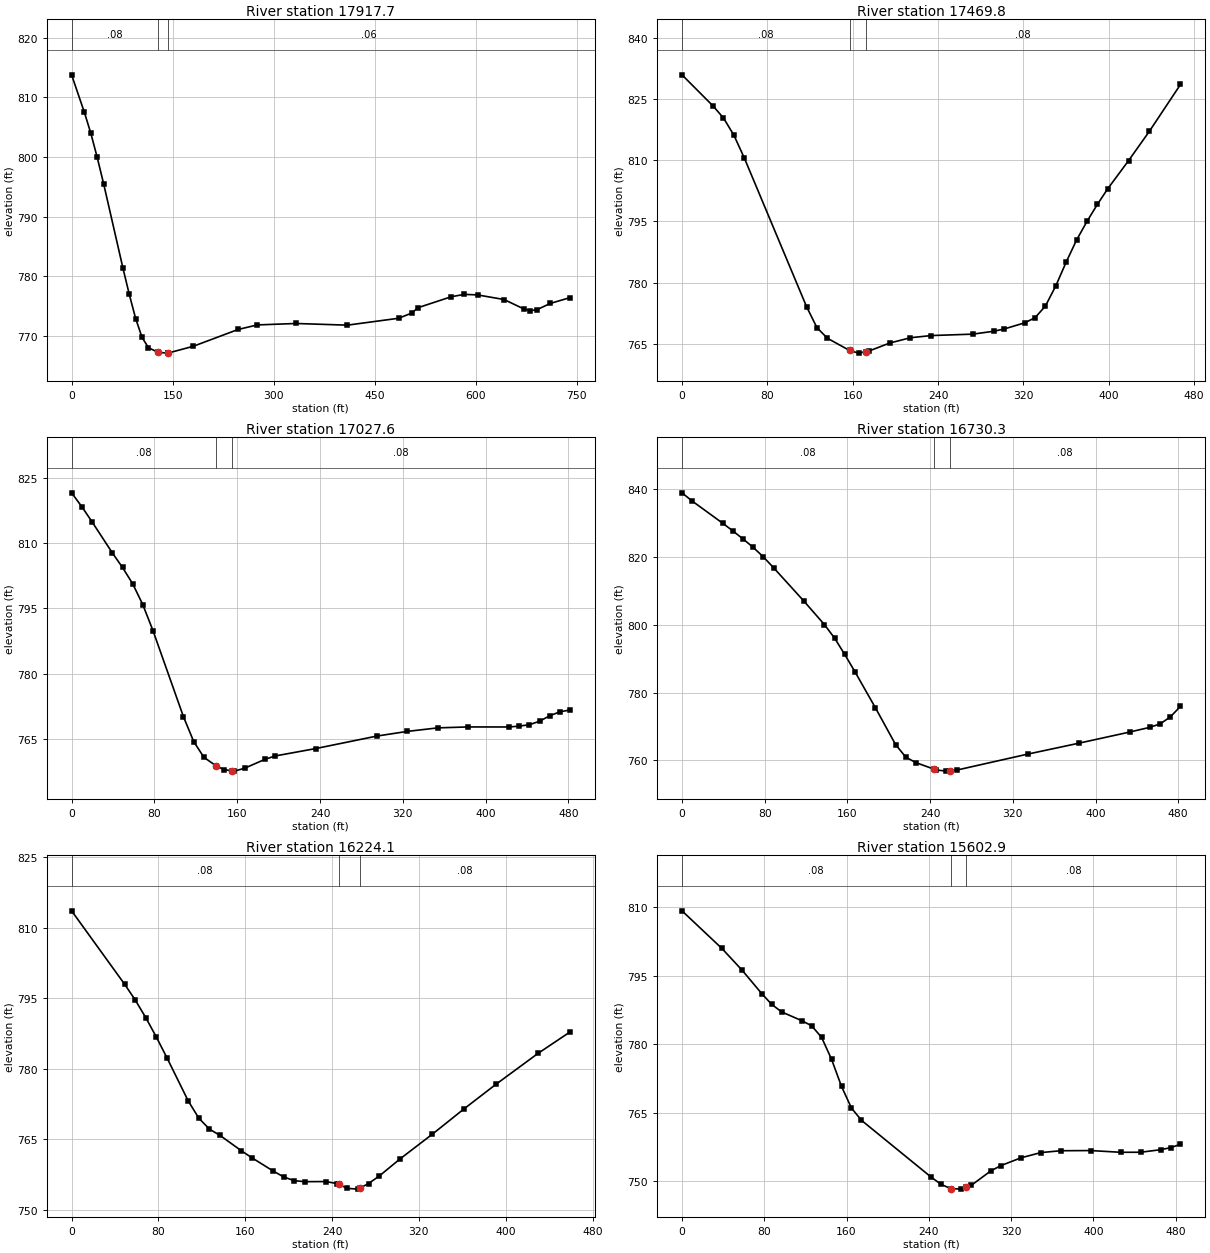
Type RM Length L Ch R = 1 ,17917.7 ,440.4,447.9,451.6
XS GIS Cut Line= 4
     1470782.752      270327.641     1470517.428       270402.93
     1470386.205      270602.246     1470189.116      270712.165
#Sta/Elev= 30
       0  813.79      19  807.49    28.5  804.01      38  799.96    47.6  795.51
    76.1  781.45    85.6     777    95.1  772.93   104.6  769.77   114.1  768.04
   128.5  767.26   142.6  767.13   143.5  767.15   180.7  768.28   247.3   771.1
   275.8  771.86   333.1   772.1   409.4  771.82   485.8  772.98   504.9  773.85
   514.4  774.75   563.5  776.58   583.1  776.98   602.7  776.89     642  776.12
   671.4  774.54   681.2  774.25     691  774.42   710.7  775.46   740.1  776.44
#Mann= 3 , 0 , 0
       0     .08       0   128.5    .045       0   143.5     .06       0
Bank Sta=128.5,143.5
XS Rating Curve= 0 ,0
Exp/Cntr=0.3,0.1

Type RM Length L Ch R = 1 ,17469.8 ,435.9,442.2,448
XS GIS Cut Line= 2
     1470715.187      269934.581     1470250.114      269978.942
#Sta/Elev= 30
       0  830.91    29.2  823.26    38.9  820.34    48.7   816.1    58.4  810.56
   116.8  774.12   126.5     769   136.3  766.41     157  763.43   165.5  762.77
     172  763.11   175.2  763.28   194.7  765.24   214.1  766.54   233.6  767.07
   272.5  767.42     292  768.12   301.7  768.66   321.2  770.19   330.9  771.44
   340.6   774.3   350.4  779.27   360.1  785.08   369.8  790.46   379.6  795.04
   389.3  799.18     399  803.01   418.5  809.89     438  817.07   467.2  828.55
#Mann= 3 , 0 , 0
       0     .08       0     157    .045       0     172     .08       0
Bank Sta=157,172
XS Rating Curve= 0 ,0
Exp/Cntr=0.3,0.1

Type RM Length L Ch R = 1 ,17027.6 ,293.7,297.3,300.4
XS GIS Cut Line= 2
     1470703.492      269599.861     1470227.677       269525.09
#Sta/Elev= 30
       0  821.49     9.8  818.34    19.7  814.87    39.3  807.76    49.2  804.39
      59  800.67    68.8  795.88    78.6  789.95   108.1  770.19     118  764.52
   127.8  760.92   139.6758.9509   147.4  758.08   154.8757.8366   157.3  757.75
   167.1  758.41   186.8  760.45   196.6  761.22   235.9  762.92   294.9  765.78
   324.4  766.85   353.9  767.66   383.4  767.87   422.7  767.86   432.5  768.06
   442.3  768.38   452.2  769.19     462  770.44   471.8  771.34   481.6  771.75
#Mann= 3 , 0 , 0
       0     .08       0   139.6    .045       0   154.8     .08       0
Bank Sta=139.6,154.8
XS Rating Curve= 0 ,0
Exp/Cntr=0.3,0.1

Type RM Length L Ch R = 1 ,16730.3 ,497.8,506.2,511.6
XS GIS Cut Line= 2
     1470832.252      269358.941     1470372.145      269214.789
#Sta/Elev= 29
       0  838.93     9.8  836.52    39.4  829.96    49.2   827.7      59  825.34
    68.9  822.84    78.7  820.04    88.6  816.84   118.1  806.94   137.8  800.06
   147.6  796.09   157.4  791.28   167.3  786.17     187  775.59   206.6   764.7
   216.5  760.97   226.3  759.36     244  757.42     246   757.2   255.8  756.86
   259.1 756.963   265.7  757.16   334.6  761.89   383.8  765.09     433  768.38
   452.6  769.78   462.5  770.79   472.3  772.83   482.2  775.96
#Mann= 3 , 0 , 0
       0     .08       0     244    .045       0   259.1     .08       0
Bank Sta=244,259.1
XS Rating Curve= 0 ,0
Exp/Cntr=0.3,0.1

Type RM Length L Ch R = 1 ,16224.1 ,623.8,621.2,597.3
XS GIS Cut Line= 2
     1470950.087      268966.773     1470567.492      268712.638
#Sta/Elev= 30
       0  813.59    48.9  797.95    58.6  794.62    68.4  790.83    78.2  786.67
      88  782.24   107.5   773.1   117.3  769.42     127  767.12   136.8  765.77
   156.4  762.51   166.1  761.02   185.7   758.2   195.4  756.94   205.2  756.13
     215  755.93   234.5  755.95   244.3  755.53     246755.3513   254.1   754.5
   263.9  754.34   265.3754.5118   273.6  755.53   283.4  757.12     303  760.84
   332.3  766.02   361.6  771.43   390.9  776.64     430  783.28   459.3  787.81
#Mann= 3 , 0 , 0
       0     .08       0     246    .045       0   265.3     .08       0
Bank Sta=246,265.3
XS Rating Curve= 0 ,0
Exp/Cntr=0.3,0.1

Type RM Length L Ch R = 1 ,15602.9 ,543.8,539.7,533.9
XS GIS Cut Line= 2
     1471154.075      268377.638     1470671.684      268424.855
#Sta/Elev= 30
       0  809.15    38.8  800.93    58.2  796.24    77.6  791.05    87.2  788.71
    96.9  787.06   116.3  785.16     126  784.04   135.7  781.51   145.4  776.72
   155.1  770.78   164.8  766.04   174.5  763.37   242.4  750.93     252  749.36
   261.2748.4598   271.4  748.33   276.4748.7383   281.1  749.13   300.5  752.35
   310.2  753.48   329.6  755.17     349  756.32   368.4  756.72   397.4  756.76
   426.5  756.38   445.9  756.39   465.3  756.94     475  757.39   484.7  758.12
#Mann= 3 , 0 , 0
       0     .08       0   261.2    .045       0   276.4     .08       0
Bank Sta=261.2,276.4
XS Rating Curve= 0 ,0
Exp/Cntr=0.3,0.1

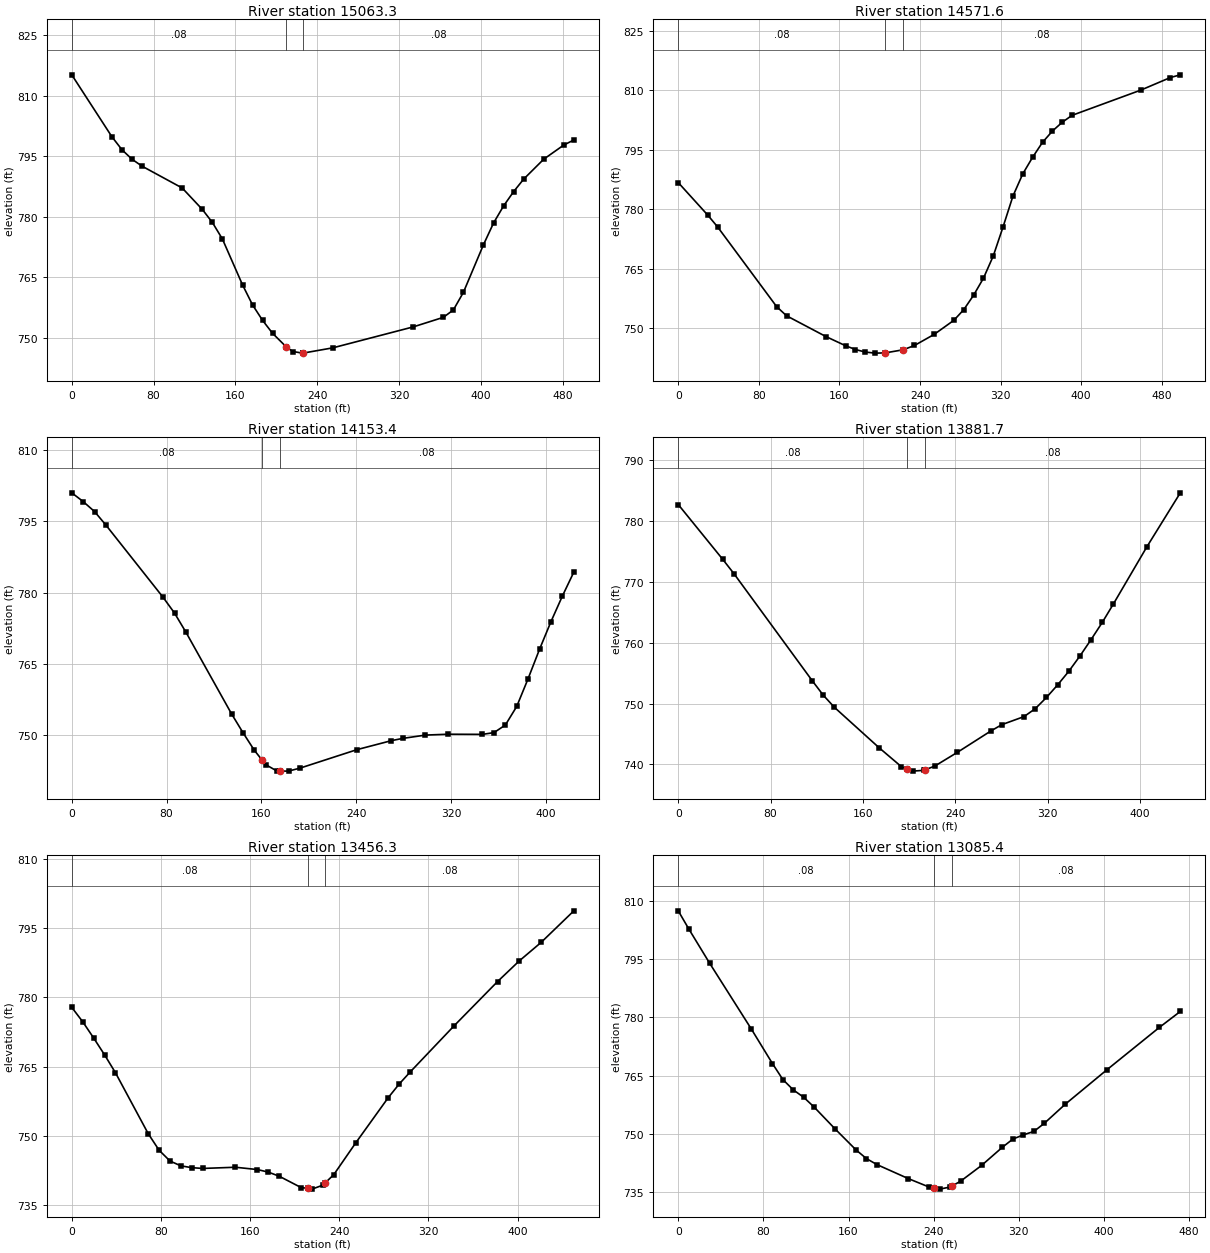
Type RM Length L Ch R = 1 ,15063.3 ,489.8,491.7,494
XS GIS Cut Line= 2
      1470879.99      267910.028     1470422.795      268089.178
#Sta/Elev= 30
       0  815.17    39.3   799.8    49.1   796.6    58.9  794.25    68.8  792.52
     108  787.12   127.7   781.8   137.5  778.58   147.3  774.48     167  763.11
   176.8  758.14   186.6  754.31   196.4  751.09   209.8747.7255   216.1  746.59
   225.9  746.19   226.3746.2018   255.3   747.5   333.9  752.69   363.4  755.06
   373.2   756.9     383  761.26   402.6  773.05   412.5  778.45   422.3  782.68
   432.1  786.22   441.9  789.31   461.6  794.27   481.2  797.77     491  799.02
#Mann= 3 , 0 , 0
       0     .08       0   209.8    .045       0   226.3     .08       0
Bank Sta=209.8,226.3
XS Rating Curve= 0 ,0
Exp/Cntr=0.3,0.1

Type RM Length L Ch R = 1 ,14571.6 ,389.6,418.2,427.4
XS GIS Cut Line= 2
     1470632.377      267526.339     1470157.978      267679.117
#Sta/Elev= 30
       0  786.72    29.3   778.5    39.1  775.51    97.7  755.37   107.5  753.07
   146.6  747.82   166.1   745.5   175.9  744.54   185.7   743.9   195.4  743.63
   205.3743.6825   223.3 744.475   234.5  745.56   254.1  748.37   273.6  751.92
   283.4   754.6   293.2  758.26     303  762.57   312.7  768.16   322.5  775.56
   332.3  783.34     342  788.91   351.8  793.12   361.6  796.88   371.4  799.72
   381.1  801.94   390.9   803.7   459.3  810.09   488.6  813.26   498.4  813.94
#Mann= 3 , 0 , 0
       0     .08       0   205.3    .045       0   223.3     .08       0
Bank Sta=205.3,223.3
XS Rating Curve= 0 ,0
Exp/Cntr=0.3,0.1

Type RM Length L Ch R = 1 ,14153.4 ,274.2,271.8,269.1
XS GIS Cut Line= 2
     1470668.252      267263.638     1470246.347       267225.13
#Sta/Elev= 30
       0  800.96     9.6  799.13    19.3     797    28.9  794.15      77  779.01
    86.7  775.68    96.3  771.67   134.8   754.5   144.4  750.56   154.1  746.81
   160.7  744.74   163.7   743.8   173.3  742.44   175.8742.4401   182.9  742.45
   192.6  743.07   240.7  746.96   269.6  748.84   279.2  749.32   298.5  750.02
   317.7   750.2   346.6  750.17   356.3  750.54   365.9  752.13   375.5  756.04
   385.1  761.88   394.8   768.1   404.4  773.88     414  779.24   423.7   784.3
#Mann= 3 , 0 , 0
       0     .08       0   160.7    .045       0   175.8     .08       0
Bank Sta=160.7,175.8
XS Rating Curve= 0 ,0
Exp/Cntr=0.3,0.1

Type RM Length L Ch R = 1 ,13881.7 ,409.6,425.3,438.3
XS GIS Cut Line= 2
     1470700.412      266976.161      1470265.72      266986.087
#Sta/Elev= 27
       0  782.69    38.6  773.67    48.3  771.32     116  753.76   125.6  751.37
   135.3  749.37   173.9  742.75   193.2  739.64   198.3739.2551   202.9   738.9
   212.6  739.03   213.7739.1145   222.2  739.73   241.6  741.97   270.6  745.48
   280.2  746.53   299.5  747.86   309.2  749.16   318.9     751   328.5  753.05
   338.2  755.29   347.8  757.79   357.5   760.5   367.2  763.32   376.8  766.34
   405.8  775.73   434.8  784.61
#Mann= 3 , 0 , 0
       0     .08       0   198.3    .045       0   213.7     .08       0
Bank Sta=198.3,213.7
XS Rating Curve= 0 ,0
Exp/Cntr=0.3,0.1

Type RM Length L Ch R = 1 ,13456.3 ,379.1,370.9,359
XS GIS Cut Line= 2
     1470747.565      266723.187     1470371.313      266475.377
#Sta/Elev= 30
       0  777.84     9.8  774.73    19.6  771.22    29.4  767.57    39.2  763.68
    68.6  750.48    78.4  746.88    88.2  744.55    97.9  743.51   107.7  743.12
   117.5  742.95   146.9  743.21   166.5  742.71   176.3  742.16   186.1  741.27
   205.7  738.82   211.7738.6105   215.5  738.47   225.3  739.33   227.2739.7764
   235.1  741.61   254.6  748.42     284   758.3   293.8  761.24   303.6  763.83
   342.8  773.78     382  783.42   401.6  787.92   421.1   791.9   450.5  798.75
#Mann= 3 , 0 , 0
       0     .08       0   211.7    .045       0   227.2     .08       0
Bank Sta=211.7,227.2
XS Rating Curve= 0 ,0
Exp/Cntr=0.3,0.1

Type RM Length L Ch R = 1 ,13085.4 ,315.1,312.9,310.7
XS GIS Cut Line= 2
     1470915.539      266502.305     1470455.803      266396.353
#Sta/Elev= 30
       0  807.55     9.8  802.92    29.5  794.02    68.8  776.97    88.5  768.11
    98.3  763.97   108.1   761.3     118  759.36   127.8  756.83   147.4  751.21
   167.1  745.78   176.9  743.54   186.8  741.99   216.2  738.38   235.9  736.18
   240.2735.9485   245.7  735.66   255.6  736.21   256.9 736.413   265.4  737.72
     285  741.77   304.7   746.5   314.5   748.6   324.4  749.68   334.2  750.57
     344  752.66   363.7   757.6     403  766.53   452.1  777.43   471.8  781.56
#Mann= 3 , 0 , 0
       0     .08       0   240.2    .045       0   256.9     .08       0
Bank Sta=240.2,256.9
XS Rating Curve= 0 ,0
Exp/Cntr=0.3,0.1

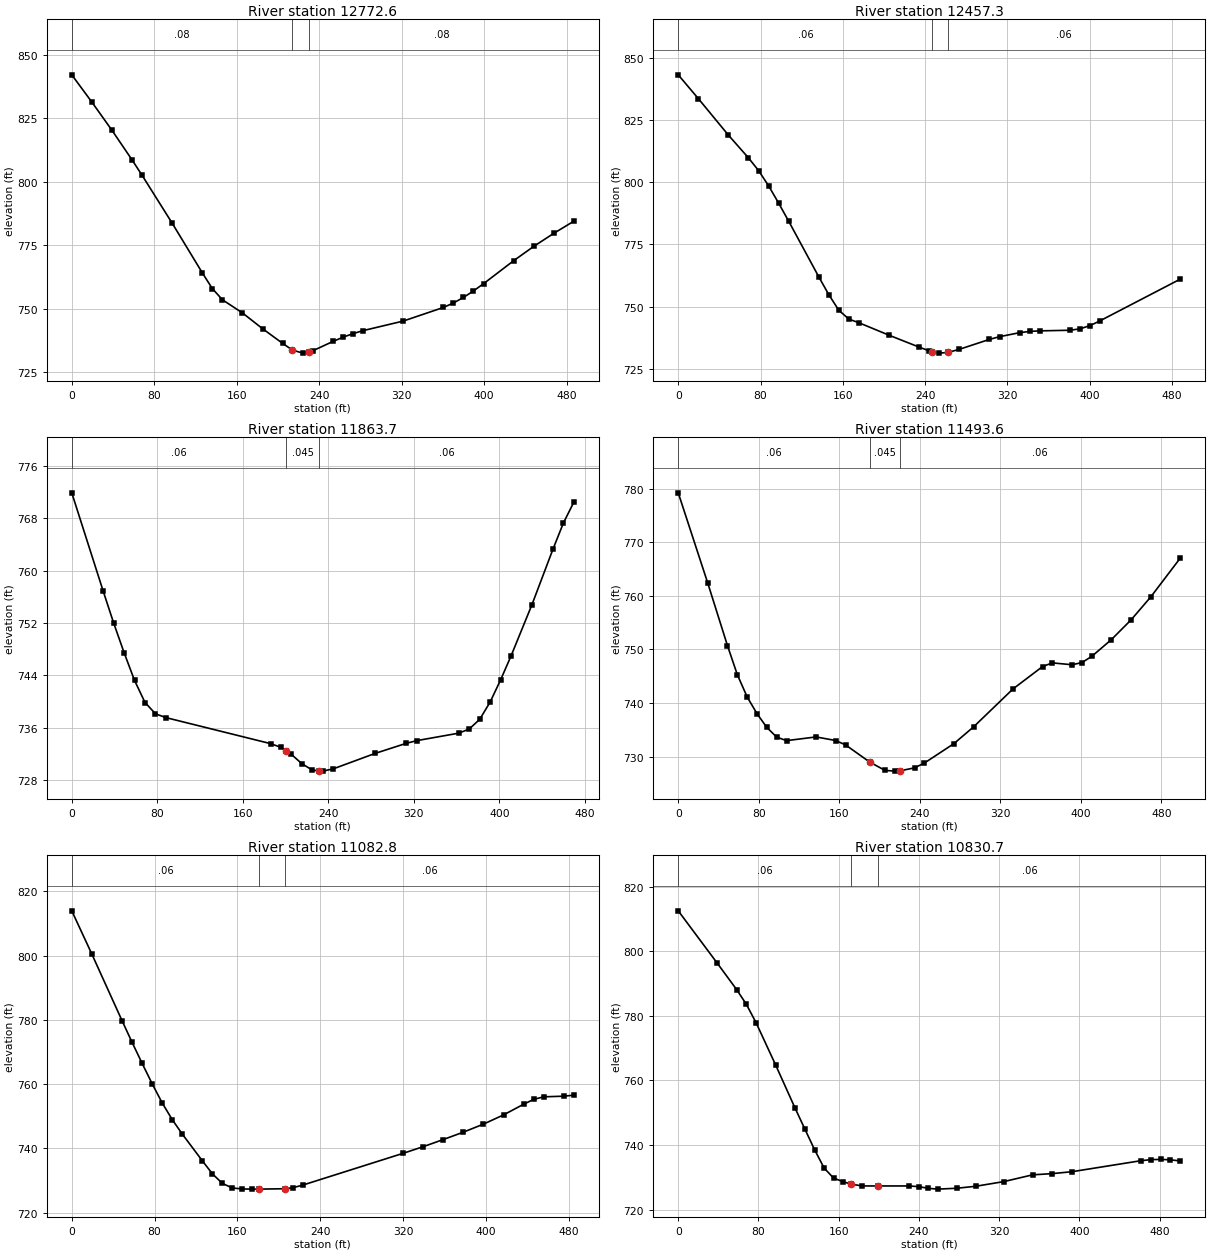
Type RM Length L Ch R = 1 ,12772.6 ,309.8,315.2,319.7
XS GIS Cut Line= 2
     1471028.989      266217.694     1470548.806      266137.115
#Sta/Elev= 30
       0  842.07    19.5  831.33      39  820.22    58.4  808.62    68.2  802.51
    97.4  783.63   126.6   764.1   136.3  757.91   146.1   753.5   165.5  748.33
     185  742.12   204.5  736.33   213.9733.7135     224  732.49   229.9733.0473
   233.7  733.41   253.2  737.07   262.9  738.73   272.7  740.16   282.4  741.34
   321.4  745.11   360.3  750.46     370  752.21   379.8   754.4   389.5  756.96
   399.3  759.82   428.5  768.87     448  774.52   467.4  779.64   486.9  784.44
#Mann= 3 , 0 , 0
       0     .08       0   213.9    .045       0   229.9     .08       0
Bank Sta=213.9,229.9
XS Rating Curve= 0 ,0
Exp/Cntr=0.3,0.1

Type RM Length L Ch R = 1 ,12457.3 ,600.7,593.6,578.7
XS GIS Cut Line= 2
     1471108.484       265975.07     1470658.038      265786.957
#Sta/Elev= 30
       0   843.3    19.5  833.74    48.8  819.02    68.3  809.86    78.1  804.77
    87.9   798.6    97.6  791.67   107.4  784.37   136.7  761.95   146.4   754.8
   156.2  748.49     166  744.95   175.7   743.5     205  738.48   234.3  733.68
   244.1  732.18   247.2  731.89   253.8  731.27   262.2  731.54   273.4  732.81
   302.6   736.8   312.4  737.89   331.9   739.5   341.7  740.01   351.5  740.23
   380.8  740.48   390.5  741.03   400.3  742.33     410  744.25   488.2  761.07
#Mann= 3 , 0 , 0
       0     .06       0   247.2    .045       0   262.2     .06       0
Bank Sta=247.2,262.2
XS Rating Curve= 0 ,0
Exp/Cntr=0.3,0.1

Type RM Length L Ch R = 1 ,11863.7 ,362.5,370.1,375.8
XS GIS Cut Line= 2
     1471128.402      265438.694     1470659.948        265470.9
#Sta/Elev= 30
       0  771.91    29.4  756.86    39.1  752.03    48.9  747.47    58.7  743.21
    68.5  739.83    78.3   738.1      88  737.52   185.9  733.54   195.6  732.97
   200.3 732.452   205.4  731.89   215.2  730.47     225  729.49   231.2729.3876
   234.8  729.33   244.6  729.68   283.7  732.04     313  733.59   322.8     734
     362  735.14   371.7  735.77   381.5  737.24   391.3   739.9   401.1  743.29
   410.9  746.97   430.4  754.79     450  763.26   459.8  767.28   469.6  770.49
#Mann= 3 , 0 , 0
       0     .06       0   200.3    .045       0   231.2     .06       0
Bank Sta=200.3,231.2
XS Rating Curve= 0 ,0
Exp/Cntr=0.3,0.1

Type RM Length L Ch R = 1 ,11493.6 ,423.5,410.8,398.1
XS GIS Cut Line= 2
     1471102.319      265261.786     1470612.801      265165.388
#Sta/Elev= 30
       0  779.23    29.4  762.35    48.9  750.73    58.7   745.3    68.5  741.14
    78.3  738.01      88  735.46    97.8  733.65   107.6  732.99     137  733.68
   156.5  733.01   166.3  732.19   190.2728.9994   205.4  727.44   215.2   727.3
   220.5 727.363   234.8  727.91   244.6  728.81   273.9  732.43   293.5  735.56
   332.6  742.63     362  746.81   371.7   747.5   391.3  747.15   401.1  747.55
   410.9  748.71   430.4  751.84     450  755.53   469.6  759.82   498.9  767.06
#Mann= 3 , 0 , 0
       0     .06       0   190.2    .045       0   220.5     .06       0
Bank Sta=190.2,220.5
XS Rating Curve= 0 ,0
Exp/Cntr=0.3,0.1

Type RM Length L Ch R = 1 ,11082.8 ,245.2,252.1,258.9
XS GIS Cut Line= 2
     1470980.775      264823.661     1470526.321      264992.429
#Sta/Elev= 30
       0  813.92    19.4  800.45    48.5  779.76    58.2  773.01    67.9  766.47
    77.6  760.11    87.3  754.13      97  748.94   106.6  744.48     126  736.15
   135.7   732.1   145.4  729.07   155.1  727.66   164.8  727.35   174.5   727.3
   181.1   727.3   205.7727.4239   213.3  727.72     223  728.55     320  738.45
   339.4  740.52   358.7  742.73   378.1  745.03   397.5  747.53   416.9   750.4
   436.3  753.72     446  755.23   455.7  756.03   475.1  756.23   484.8  756.54
#Mann= 3 , 0 , 0
       0     .06       0   181.1    .045       0   205.7     .06       0
Bank Sta=181.1,205.7
XS Rating Curve= 0 ,0
Exp/Cntr=0.3,0.1

Type RM Length L Ch R = 1 ,10830.7 ,74.7,78.8,82.4
XS GIS Cut Line= 4
     1470932.973      264686.897     1470804.042      264643.492
     1470587.105      264655.313     1470461.244       264732.11
#Sta/Elev= 30
       0  812.48    38.9  796.28    58.3  788.07      68  783.51    77.7   777.8
    97.2  764.71   116.6  751.34   126.3   744.9     136  738.51   145.5  732.84
   154.9  729.75   164.4  728.61   172.4727.8866   183.3   727.3   199.6   727.3
   230.5   727.3     240  727.08   249.4  726.57   258.8  726.32   277.7  726.59
   296.6   727.2     325  728.67   353.3  730.74     373  731.12   392.6  731.71
   461.4  735.12   471.2  735.44   481.1  735.53   490.9  735.39   500.7  735.04
#Mann= 3 , 0 , 0
       0     .06       0   172.4    .045       0   199.6     .06       0
Bank Sta=172.4,199.6
XS Rating Curve= 0 ,0
Exp/Cntr=0.3,0.1

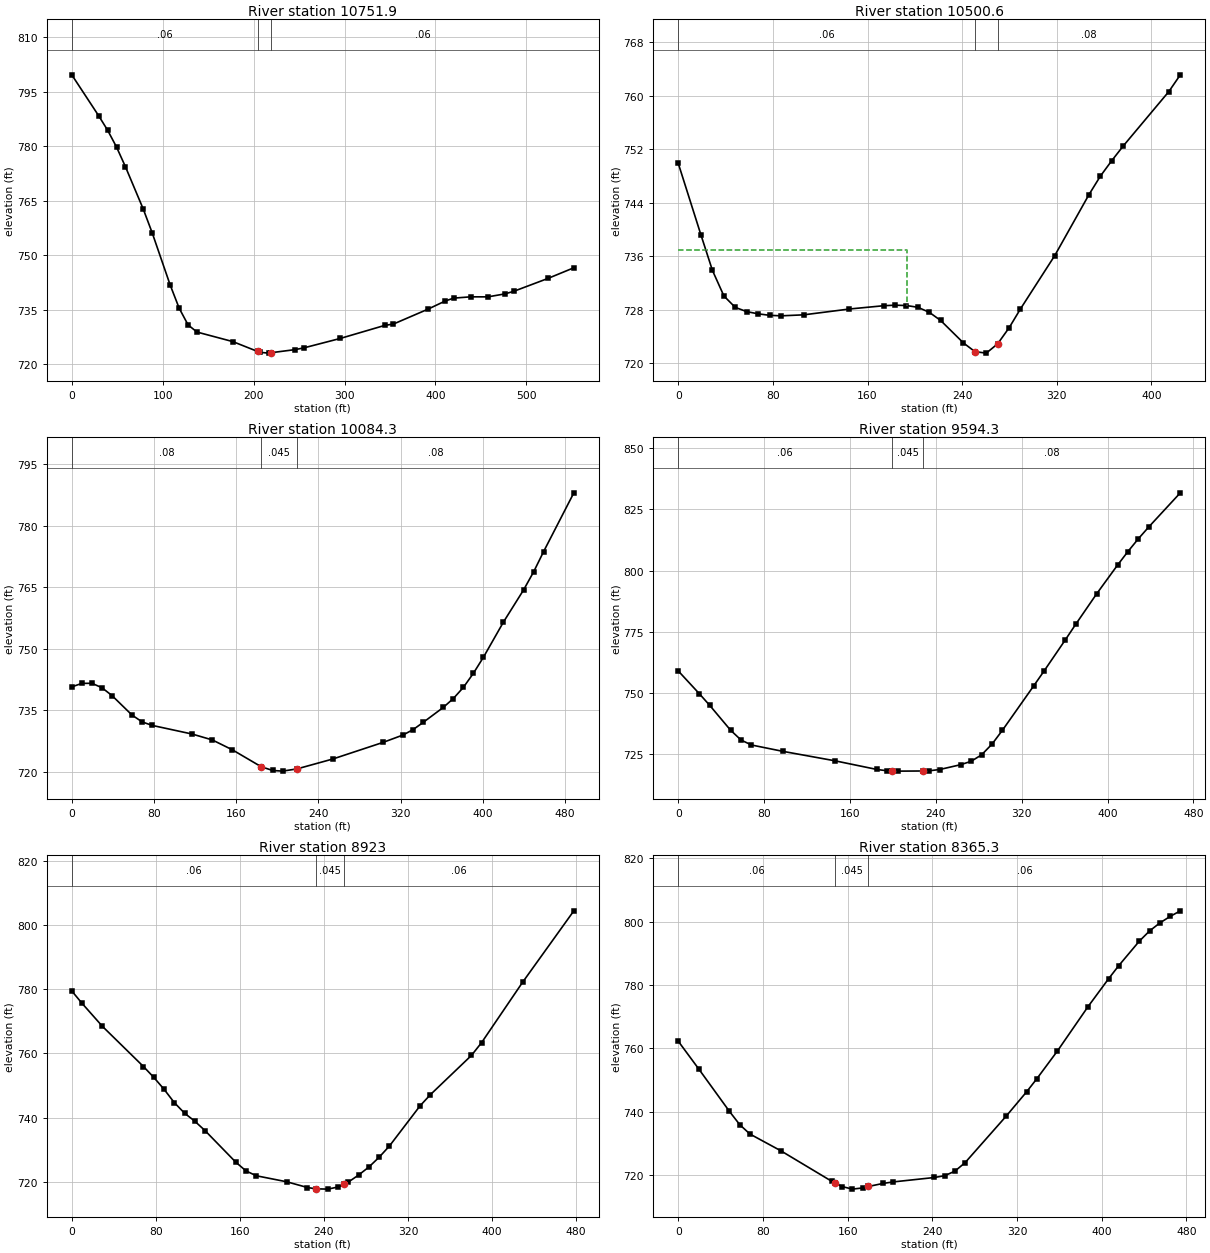
Type RM Length L Ch R = 1 ,10751.9 ,240.1,251.4,261
XS GIS Cut Line= 3
     1470942.931      264594.881     1470600.917      264554.951
     1470424.133      264664.327
#Sta/Elev= 30
       0   799.7    29.5  788.45    39.4  784.44    49.2  779.81      59  774.38
    78.7  762.64    88.5  756.11   108.2  741.78   118.1  735.38   127.9  730.77
   137.7  728.79   177.1  726.16   204.4  723.44   206.6  723.21   216.4  722.98
   219.4   723.1     246  723.96   255.8  724.46   295.2  727.02   344.3  730.63
   353.8     731   391.6  735.08   410.5  737.32   419.9  738.14   438.8   738.5
   457.7  738.49   476.6  739.32   486.1  740.02   523.9  743.59   552.2  746.51
#Mann= 3 , 0 , 0
       0     .06       0   204.4    .045       0   219.4     .06       0
Bank Sta=204.4,219.4
XS Rating Curve= 0 ,0
Exp/Cntr=0.3,0.1

Type RM Length L Ch R = 1 ,10500.6 ,414.3,416.3,403.1
XS GIS Cut Line= 2
     1470912.024      264479.563     1470545.243      264266.141
#Sta/Elev= 30
       0  749.88    19.3  739.12    28.9  733.88    38.6  730.06    48.2  728.35
    57.9  727.72    67.5  727.39    77.2  727.17    86.8  727.09   106.1  727.24
   144.7  728.11   173.6   728.6   183.2  728.68   192.9  728.63   202.5  728.37
   212.2  727.62   221.8   726.4   241.1  723.04   250.8  721.74   260.4  721.52
     270  722.91   279.7  725.31   289.3  728.13   318.3   736.1   347.2   745.2
   356.8  747.95   366.5  750.28   376.1  752.45   414.7  760.59   424.4  763.09
#Mann= 3 , 0 , 0
       0     .06       0   250.8    .045       0     270     .08       0
#XS Ineff= 2 , 0
          193.53  736.94
Permanent Ineff=
       F       F
Bank Sta=250.8,270
XS Rating Curve= 0 ,0
Exp/Cntr=0.3,0.1

Type RM Length L Ch R = 1 ,10084.3 ,481.5,490,498.2
XS GIS Cut Line= 2
     1471130.246      264239.094     1470670.294      264074.078
#Sta/Elev= 30
       0  740.69     9.8  741.55    19.6  741.57    29.3   740.5    39.1  738.59
    58.6  733.83    68.4  732.16    78.2   731.3   117.3  729.18   136.8  727.75
   156.4  725.33   184.4721.2118   195.5   720.3   205.2  720.14   219.2720.6815
   254.1   723.1     303  727.15   322.5  728.96   332.3  730.28   342.1  732.04
   361.6  735.68   371.4  737.85   381.2  740.58   390.9     744   400.7  747.93
   420.2  756.52   439.8  764.36   449.6  768.78   459.3  773.72   488.7  788.04
#Mann= 3 , 0 , 0
       0     .08       0   184.4    .045       0   219.2     .08       0
Bank Sta=184.4,219.2
XS Rating Curve= 0 ,0
Exp/Cntr=0.3,0.1

Type RM Length L Ch R = 1 ,9594.3  ,669.5,671.4,589.3
XS GIS Cut Line= 2
     1471223.567      263886.437     1470788.228      263715.294
#Sta/Elev= 30
       0   759.1    19.5  749.87    29.2  745.11    48.7  734.94    58.5   730.9
    68.2  728.87    97.4  726.28   146.2   722.4   185.2  718.87   194.9  718.33
   199.3718.2711   204.6   718.2   228.3 718.258   233.9  718.34   243.6  718.86
   263.1  720.82   272.9  722.21   282.6  724.84   292.4  729.24   302.1  734.91
   331.3  753.06   341.1  759.22   360.6  771.74   370.3   778.1   389.8  790.54
   409.3  802.28     419  807.84   428.8  813.09   438.5  817.91   467.8  831.79
#Mann= 3 , 0 , 0
       0     .06       0   199.3    .045       0   228.3     .08       0
Bank Sta=199.3,228.3
XS Rating Curve= 0 ,0
Exp/Cntr=0.3,0.1

Type RM Length L Ch R = 1 ,8923    ,560.9,557.6,549.8
XS GIS Cut Line= 2
     1471429.398      263515.778     1470994.371       263318.23
#Sta/Elev= 30
       0  779.46     9.8   775.6    29.2  768.43    68.2  755.93      78  752.57
    87.8  748.85    97.5  744.72   107.3   741.4     117  738.92   126.8  735.97
     156  726.16   165.8  723.42   175.5  721.91   204.8  720.01   224.3  718.24
   232.3717.8359   243.8  717.74   253.5  718.42   258.8719.2529   263.3  719.96
     273  722.14   282.8  724.64   292.5  727.67   302.3  731.17   331.5   743.7
   341.3  747.17   380.3  759.37     390  763.37     429  782.16   477.8  804.42
#Mann= 3 , 0 , 0
       0     .06       0   232.3    .045       0   258.8     .06       0
Bank Sta=232.3,258.8
XS Rating Curve= 0 ,0
Exp/Cntr=0.3,0.1

Type RM Length L Ch R = 1 ,8365.3  ,452,452.1,445.7
XS GIS Cut Line= 2
     1471577.739      263081.165     1471135.571       262909.87
#Sta/Elev= 30
       0  762.29    19.4  753.51    48.4  740.12    58.1  735.94    67.7  732.99
    96.8  727.72   145.2  718.03   148.4717.4901   154.8  716.41   164.5   715.6
   174.2  715.98   179.6716.4343   193.6  717.41   203.2  717.88   241.9  719.27
   251.6  719.83   261.3  721.27     271  723.98   309.7  738.62     329   746.3
   338.7  750.44   358.1  759.18   387.1  773.22   406.4  781.97   416.1  786.15
   435.5  793.87   445.2  797.09   454.8  799.59   464.5  801.64   474.2  803.43
#Mann= 3 , 0 , 0
       0     .06       0   148.4    .045       0   179.6     .06       0
Bank Sta=148.4,179.6
XS Rating Curve= 0 ,0
Exp/Cntr=0.3,0.1

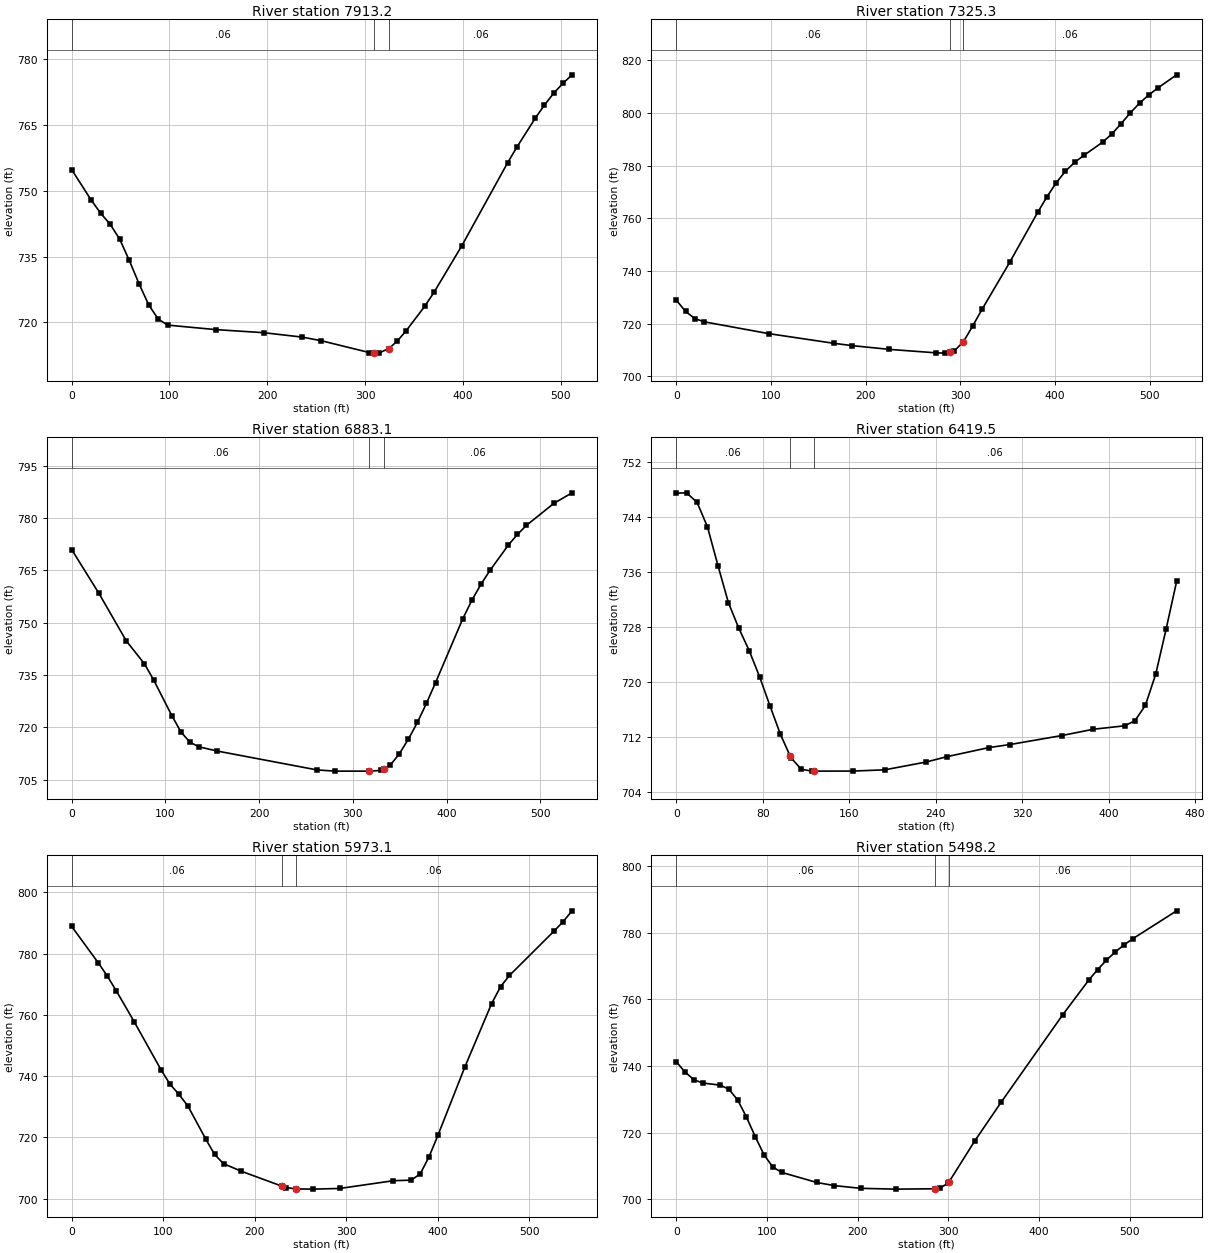
Type RM Length L Ch R = 1 ,7913.2  ,590.6,587.9,586.1
XS GIS Cut Line= 3
     1471720.665      262721.733     1471427.306       262640.02
     1471220.709      262626.131
#Sta/Elev= 30
       0  754.85    19.6  748.02    29.5  744.94    39.3   742.4    49.1  738.99
    58.9  734.13    68.8  728.86    78.6  724.08    88.4  720.77    98.2  719.39
   147.4  718.36   196.5  717.66   235.8  716.65   255.4  715.82   304.5  713.12
   309.1713.0613   313.9     713   324.2  714.02   332.8  715.72   342.2  718.16
     361  723.69   370.4  726.84   398.6  737.37   445.7   756.4   455.1  759.95
   473.9  766.55   483.4  769.57   492.8  772.27   502.2   774.5   511.6  776.47
#Mann= 3 , 0 , 0
       0     .06       0   309.1    .045       0   324.2     .06       0
Bank Sta=309.1,324.2
XS Rating Curve= 0 ,0
Exp/Cntr=0.3,0.1

Type RM Length L Ch R = 1 ,7325.3  ,442.6,442.2,441.2
XS GIS Cut Line= 2
     1471678.737       262195.42     1471151.741      262159.629
#Sta/Elev= 30
       0  728.99     9.8  724.72    19.6  721.99    29.4  720.76    97.8  716.26
   166.3   712.6   185.8  711.71     225  710.29   273.9  708.99   283.7  708.87
   289.3709.3256   293.4  709.66   303.2  713.22     313  719.21   322.8  725.49
   352.1   743.4   381.5  762.27   391.3  768.18     401  773.46   410.8  777.91
   420.6   781.3   430.4  783.95     450  788.91   459.7     792   469.5   795.9
   479.3  800.03   489.1  803.75   498.9  806.89   508.6  809.56   528.2   814.5
#Mann= 3 , 0 , 0
       0     .06       0   289.3    .045       0   303.2     .06       0
Bank Sta=289.3,303.2
XS Rating Curve= 0 ,0
Exp/Cntr=0.3,0.1

Type RM Length L Ch R = 1 ,6883.1  ,457.9,463.6,469
XS GIS Cut Line= 2
     1471684.233      261766.995     1471150.624      261754.044
#Sta/Elev= 30
       0  770.95    29.1  758.39    58.2  744.82    77.6  738.24    87.3  733.69
   106.8  723.41   116.5  718.75   126.2  715.75   135.9  714.45   155.3  713.25
     262  707.83   281.4   707.5   317.4   707.5     330   707.7     333 708.145
   339.7  709.15   349.4  712.39   359.1   716.6   368.8  721.45   378.5  726.92
   388.2  732.86   417.3  751.18     427  756.47   436.7  761.04   446.4  765.04
   465.8  772.22   475.5  775.28   485.2  777.89   514.4  784.18   533.8   787.2
#Mann= 3 , 0 , 0
       0     .06       0   317.4    .045       0     333     .06       0
Bank Sta=317.4,333
XS Rating Curve= 0 ,0
Exp/Cntr=0.3,0.1

Type RM Length L Ch R = 1 ,6419.5  ,451.1,446.4,439.4
XS GIS Cut Line= 2
     1471645.271      261429.234     1471199.899      261303.115
#Sta/Elev= 30
       0  747.47     9.6  747.52    19.3  746.12    28.9  742.56    38.6  736.94
    48.2  731.59    57.9  727.84    67.5   724.6    77.2  720.76    86.8  716.54
    96.4  712.43   105.3 709.315   106.1  709.04   115.7  707.37   125.4   707.1
   127.4   707.1   163.9  707.11   192.9  707.29   231.4  708.43   250.7  709.21
   289.3  710.52   308.6  710.96   356.8  712.27   385.7  713.18   414.7  713.68
   424.3  714.41     434  716.65   443.6   721.2   453.2  727.74   462.9  734.65
#Mann= 3 , 0 , 0
       0     .06       0   105.3    .045       0   127.4     .06       0
Bank Sta=105.3,127.4
XS Rating Curve= 0 ,0
Exp/Cntr=0.3,0.1

Type RM Length L Ch R = 1 ,5973.1  ,471.1,474.9,476.4
XS GIS Cut Line= 2
     1471768.101       261019.29     1471223.301      260971.598
#Sta/Elev= 30
       0   788.9    29.3  776.92    39.1  772.62    48.8  767.85    68.4  757.74
    97.7  742.05   107.4  737.39   117.2  734.06     127  730.25   146.5  719.47
   156.2  714.44     166   711.4   185.6  708.92   229.9704.0496   234.4  703.62
     245  703.17   263.7   703.1     293  703.32   351.6  705.85   371.1  706.03
   380.9  708.06   390.6  713.65   400.4  720.74   429.7  742.96     459  763.71
   468.8  769.23   478.5  772.89   527.4  787.43   537.1  790.44   546.9     794
#Mann= 3 , 0 , 0
       0     .06       0   229.9    .045       0     245     .06       0
Bank Sta=229.9,245
XS Rating Curve= 0 ,0
Exp/Cntr=0.3,0.1

Type RM Length L Ch R = 1 ,5498.2  ,378.7,388.8,398.2
XS GIS Cut Line= 2
     1471735.115       260675.54     1471189.976      260590.471
#Sta/Elev= 30
       0  741.32     9.7   738.2    19.4  735.94      29  734.92    48.4  734.29
    58.1  733.05    67.8   729.8    77.4  724.71    87.1  718.84    96.8  713.38
   106.5  709.72   116.2  708.13   154.9  705.09   174.2  704.16   203.3  703.34
     242   703.1   285.6703.2057   290.4  703.31   300.1  704.98   300.9 705.323
   329.1  717.54   358.1  729.11   425.9   755.3   454.9  765.81   464.6  768.94
   474.3  771.75     484  774.22   493.7  776.33   503.3  778.17   551.7  786.56
#Mann= 3 , 0 , 0
       0     .06       0   285.6    .045       0   300.9     .06       0
Bank Sta=285.6,300.9
XS Rating Curve= 0 ,0
Exp/Cntr=0.3,0.1

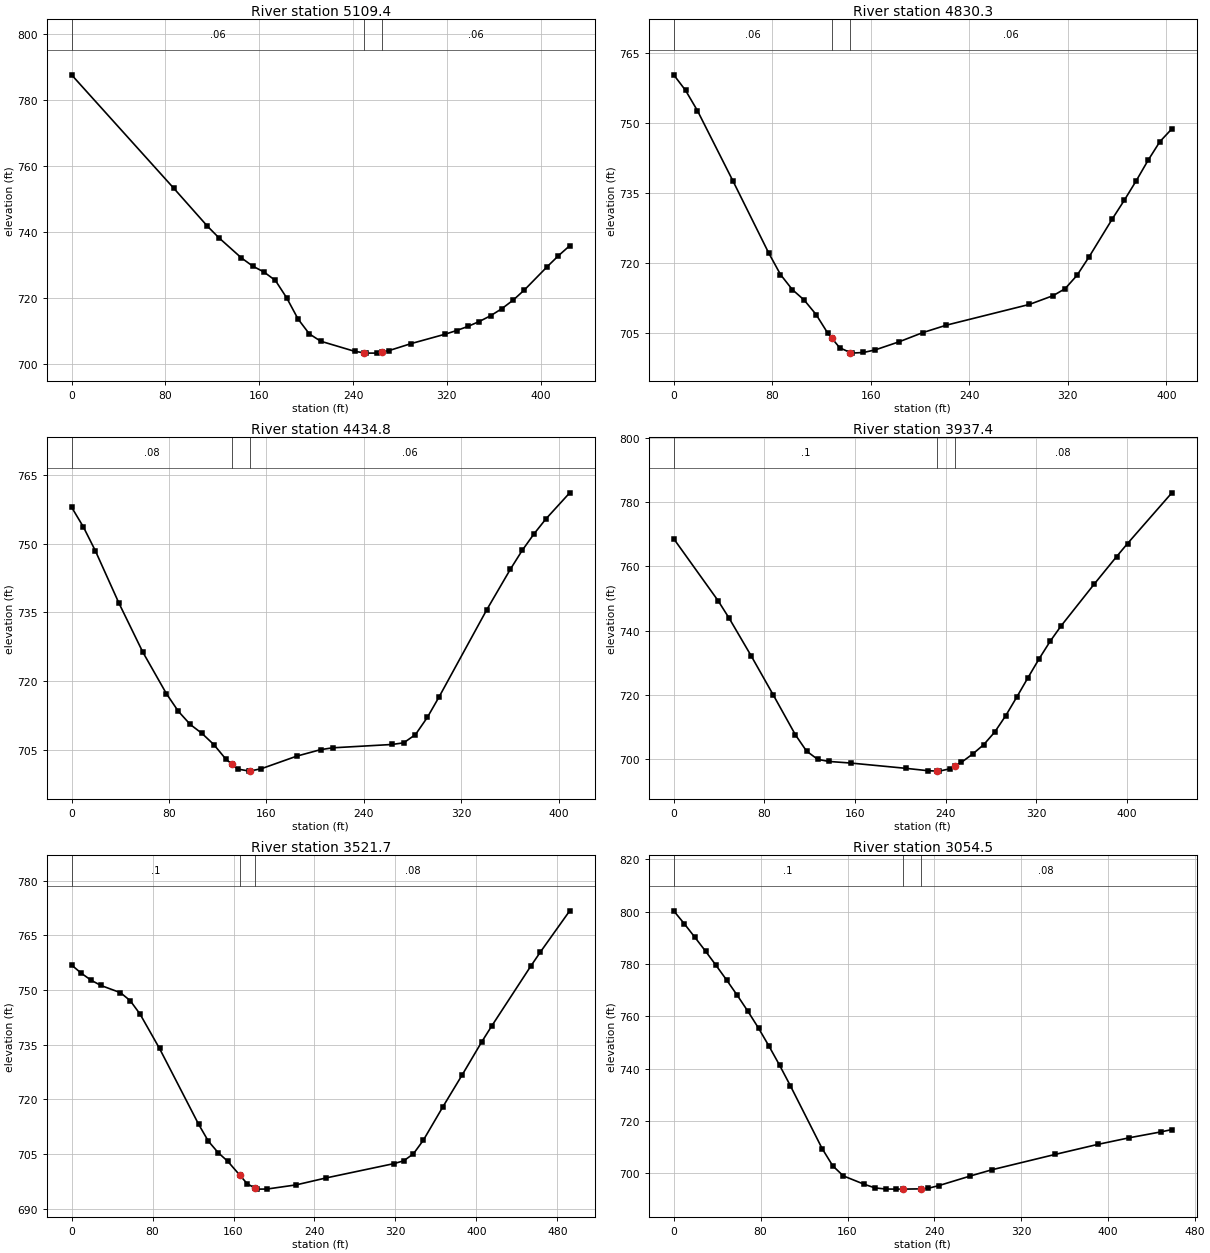
Type RM Length L Ch R = 1 ,5109.4  ,293.9,279.1,263.2
XS GIS Cut Line= 2
     1471876.635      260484.144     1471521.128      260251.718
#Sta/Elev= 30
       0  787.62    86.9  753.34   115.8  741.76   125.5  738.28   144.8  732.14
   154.4  729.67   164.1  727.85   173.8   725.3   183.4  720.04   193.1  713.62
   202.7  709.12   212.4   706.9   241.3  703.84   249.4703.3856     251  703.29
   260.6   703.3   264.5  703.59   270.3  704.02   289.6  706.19   318.6  709.04
   328.2  710.13   337.9  711.38   347.5  712.86   357.2  714.61   366.8  716.75
   376.5  719.36   386.1  722.44   405.4  729.45   415.1  732.81   424.7  735.84
#Mann= 3 , 0 , 0
       0     .06       0   249.4    .045       0   264.5     .06       0
Bank Sta=249.4,264.5
XS Rating Curve= 0 ,0
Exp/Cntr=0.3,0.1

Type RM Length L Ch R = 1 ,4830.3  ,403,395.5,387.7
XS GIS Cut Line= 2
     1471922.342      260096.029     1471519.856      260136.048
#Sta/Elev= 30
       0  760.31     9.6  756.98    19.3   752.6    48.2  737.48      77  722.14
    86.7  717.45    96.3  714.22   105.9  711.98   115.6  708.87   125.2  704.82
   128.2703.8523   134.8  701.73   143.3  700.71   144.4  700.58   154.1  700.72
   163.7  701.28     183  703.01   202.2  704.98   221.5  706.59   288.9  711.04
   308.2  712.93   317.8  714.41   327.4  717.25   337.1  721.16   356.3  729.45
     366  733.44   375.6  737.59   385.2  741.97   394.8  745.98   404.5  748.72
#Mann= 3 , 0 , 0
       0     .06       0   128.2    .045       0   143.3     .06       0
Bank Sta=128.2,143.3
XS Rating Curve= 0 ,0
Exp/Cntr=0.3,0.1

Type RM Length L Ch R = 1 ,4434.8  ,489.9,497.4,504.6
XS GIS Cut Line= 2
     1471831.393      259674.394      1471461.83      259849.342
#Sta/Elev= 30
       0  758.01     9.7  753.68    19.5  748.49    38.9  737.02    58.4  726.37
    77.9  717.23    87.6  713.42    97.4  710.53   107.1  708.56   116.8  706.12
   126.6  702.97   131.5701.8724   136.3  700.79     146  700.33   146.6  700.36
   155.8  700.86     185  703.62   204.4  705.02   214.2  705.42   262.8  706.15
   272.6  706.51   282.3  708.32   292.1   712.1   301.8  716.61   340.7  735.54
   360.2  744.45   369.9  748.56   379.7  752.21   389.4  755.45   408.9  761.14
#Mann= 3 , 0 , 0
       0     .08       0   131.5    .045       0   146.6     .06       0
Bank Sta=131.5,146.6
XS Rating Curve= 0 ,0
Exp/Cntr=0.3,0.1

Type RM Length L Ch R = 1 ,3937.4  ,418.2,415.7,410.2
XS GIS Cut Line= 2
      1471695.13      259326.655     1471259.156       259382.15
#Sta/Elev= 30
       0  768.63    39.1  749.37    48.8  743.96    68.4  732.15    87.9  719.98
   107.4   707.6   117.2  702.55     127  699.99   136.7  699.34   156.3  698.83
   205.1  697.18   224.6  696.44   232.2 696.345   234.4  696.32   244.2   697.1
   247.9 697.851   253.9  699.07   263.7  701.62   273.5  704.55   283.2  708.47
     293  713.61   302.8  719.44   312.5  725.36   322.3  731.22   332.1   736.7
   341.8  741.52   371.1  754.56   390.7  763.05   400.4  767.14   439.5  782.91
#Mann= 3 , 0 , 0
       0      .1       0   232.2    .045       0   247.9     .08       0
Bank Sta=232.2,247.9
XS Rating Curve= 0 ,0
Exp/Cntr=0.3,0.1

Type RM Length L Ch R = 1 ,3521.7  ,456.9,467.3,467.7
XS GIS Cut Line= 2
     1471681.607       258973.93     1471203.685       259091.83
#Sta/Elev= 30
       0  756.87     9.6  754.62    19.3   752.7      29  751.26    48.3  749.28
    57.9   747.1    67.6  743.43    86.9  733.97   125.5  713.19   135.1  708.56
   144.8   705.4   154.4  702.99     166 699.282   173.7   696.8   181.2695.7052
   183.4  695.38     193   695.4     222  696.55     251  698.42   318.5  702.38
   328.2  703.15   337.8  705.08   347.5  708.77   366.8  717.93   386.1  726.79
   405.4  735.85     415  740.08   453.6  756.51   463.3  760.47   492.2  771.74
#Mann= 3 , 0 , 0
       0      .1       0     166    .045       0   181.2     .08       0
Bank Sta=166,181.2
XS Rating Curve= 0 ,0
Exp/Cntr=0.3,0.1

Type RM Length L Ch R = 1 ,3054.5  ,349.5,357.8,365.1
XS GIS Cut Line= 2
     1471556.762      258577.167     1471106.559      258664.757
#Sta/Elev= 30
       0  800.35     9.8  795.37    19.5  790.22    29.3  784.92      39  779.47
    48.8  773.83    58.6  767.98    68.3  761.92    78.1  755.47    87.8  748.53
    97.6  741.19   107.3  733.52   136.6  709.44   146.4  702.82   156.1  698.97
   175.6  695.72   185.4  694.36   195.2  693.94   204.9   693.9   210.8   693.9
   227.3 694.003   234.2  694.21     244  695.24   273.2  698.94   292.8  701.29
   351.3  707.19   390.3     711   419.6  713.56   448.9  715.82   458.6  716.68
#Mann= 3 , 0 , 0
       0      .1       0   210.8    .045       0   227.3     .08       0
Bank Sta=210.8,227.3
XS Rating Curve= 0 ,0
Exp/Cntr=0.3,0.1