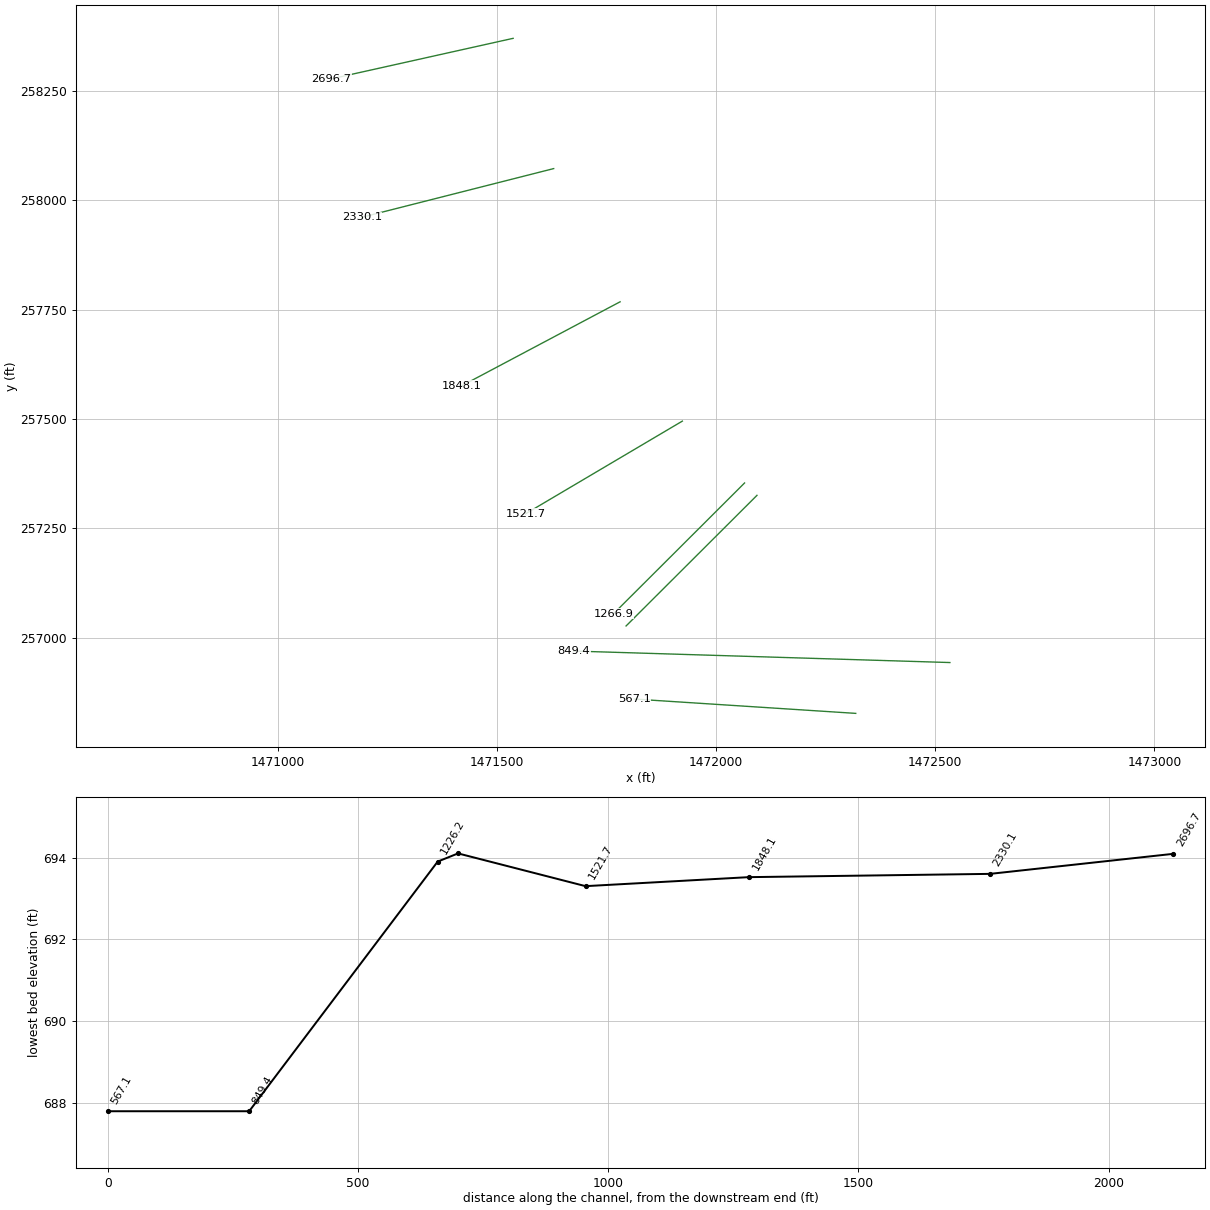
HEC-RAS study MYRSFR.prj: MYRSFR

--- MYRSFR.g01 (geometry) --- (continued)

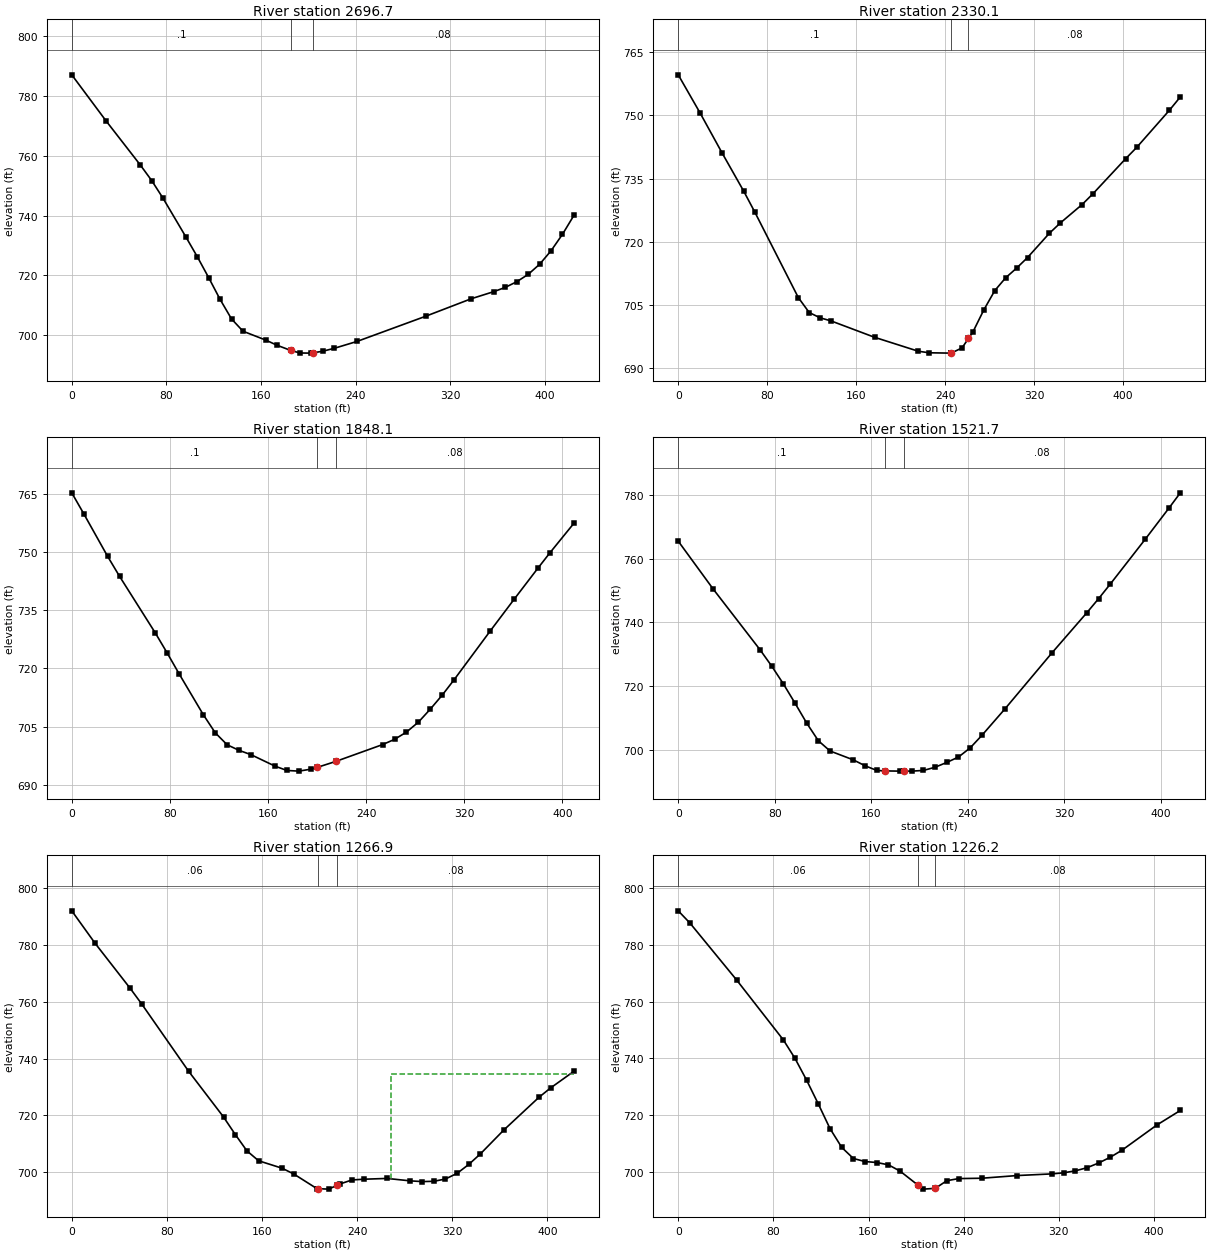
Type RM Length L Ch R = 1 ,2696.7  ,364,366.6,364.7
XS GIS Cut Line= 2
     1471537.237      258370.141     1471122.837      258277.586
#Sta/Elev= 30
       0  786.94      29  771.57    57.9  756.89    67.6  751.66    77.2  745.76
    96.5  732.86   106.2  726.22   115.8  719.26   125.4  712.04   135.1   705.5
   144.8   701.4     164  698.45   173.7   696.7   185.3694.9741     193  694.14
     202  694.09   203.6 694.156   212.3  694.73     222   695.7   241.3     698
   299.2  706.38   337.8  712.23   357.1  714.63   366.7  716.04   376.4  717.93
     386  720.37   395.7  723.76   405.3  728.23     415  733.74   424.6  740.01
#Mann= 3 , 0 , 0
       0      .1       0   185.3    .045       0   203.6     .08       0
Bank Sta=185.3,203.6
XS Rating Curve= 0 ,0
Exp/Cntr=0.3,0.1

Type RM Length L Ch R = 1 ,2330.1  ,475.6,482,474.1
XS GIS Cut Line= 2
     1471629.691      258072.422     1471192.102      257961.115
#Sta/Elev= 30
       0  759.58    19.6  750.56    39.3  741.12    58.9  731.99    68.7  727.12
     108  706.76   117.8  703.22   127.6  701.97   137.4  701.24   176.7  697.34
     216  694.04   225.8  693.68   245.3693.6001   245.4   693.6   255.2  694.84
     261697.0758     265  698.62   274.8  703.85   284.7  708.44   294.5  711.48
   304.3  713.76   314.1  716.26   333.7     722   343.6  724.46   363.2  728.83
     373   731.4   402.4  739.71   412.3  742.38   441.7  751.18   451.5  754.34
#Mann= 3 , 0 , 0
       0      .1       0   245.3    .045       0     261     .08       0
Bank Sta=245.3,261
XS Rating Curve= 0 ,0
Exp/Cntr=0.3,0.1

Type RM Length L Ch R = 1 ,1848.1  ,324.7,326.5,326.8
XS GIS Cut Line= 2
     1471781.186       257767.98     1471419.676       257575.87
#Sta/Elev= 30
       0  765.18     9.8  759.78    29.2  748.84      39  743.66    68.2  729.06
      78  723.83    87.7  718.48   107.2  708.08     117  703.39   126.7   700.3
   136.5  698.86   146.2  697.75   165.7  694.81   175.4  693.69   185.2  693.52
   194.9  694.02   200.3   694.5   215.3  696.02   253.4  700.35   263.2   701.7
   272.9  703.57   282.7  706.15   292.4   709.5   302.2  713.14   311.9  717.11
   341.2   729.6   360.6  737.73   380.1  745.78   389.9  749.74   409.4  757.32
#Mann= 3 , 0 , 0
       0      .1       0   200.3    .045       0   215.3     .08       0
Bank Sta=200.3,215.3
XS Rating Curve= 0 ,0
Exp/Cntr=0.3,0.1

Type RM Length L Ch R = 1 ,1521.7  ,248.1,254.8,259.7
XS GIS Cut Line= 2
     1471923.228      257495.299     1471565.286      257283.264
#Sta/Elev= 30
       0  765.51      29  750.45    67.7  731.45    77.4  726.31    87.1   720.7
    96.8  714.62   106.4  708.41   116.1  702.84   125.8  699.62   145.1  696.83
   154.8  694.98   164.5  693.52   171.5693.3644   183.8   693.3   186.8   693.3
   193.5   693.3   203.2  693.52   212.8  694.52   222.5  696.03   232.2  697.73
   241.9   700.6   251.6  704.53   270.9  712.93   309.6  730.41   338.6  743.06
   348.3  747.46     358  752.05     387  766.15   406.4   775.8     416  780.69
#Mann= 3 , 0 , 0
       0      .1       0   171.5    .045       0   186.8     .08       0
Bank Sta=171.5,186.8
XS Rating Curve= 0 ,0
Exp/Cntr=0.3,0.1

Type RM Length L Ch R = 1 ,1266.9  ,40.7,40.7,40.7
XS GIS Cut Line= 2
     1472065.106      257353.889     1471766.533      257055.337
#Sta/Elev= 30
       0  791.94    19.6  780.53    49.1   764.7    58.9  759.14    98.2  735.57
   127.6  719.47   137.5   713.3   147.3  707.55   157.1  704.07   176.8  701.46
   186.6  699.44   206.2  694.26   207.1694.2462     216   694.1   222.9695.4064
   225.8  695.96   235.7  697.33   245.5  697.58   265.1  697.86   284.8     697
   294.6  696.75   304.4  696.85   314.2  697.66     324  699.64   333.9   702.8
   343.7  706.52   363.3  714.88   392.8  726.36   402.6  729.66   422.2  735.51
#Mann= 3 , 0 , 0
       0     .06       0   207.1    .045       0   222.9     .08       0
#XS Ineff= 2 , 0
                          268.48          734.66
Permanent Ineff=
       F       F
Bank Sta=207.1,222.9
XS Rating Curve= 0 ,0
Exp/Cntr=0.3,0.1

Type RM Length L Ch R = 1 ,1226.2  ,394.7,376.8,404.3
XS GIS Cut Line= 2
      1472093.39      257325.603     1471794.817      257027.052
#Sta/Elev= 30
       0  791.97     9.8  787.68    49.1   767.6    88.4  746.48    98.2  739.96
     108  732.26   117.8   723.9   127.6  715.25   137.5   708.6   147.3  704.69
   157.1  703.62   166.9  703.28   176.8  702.46   186.6  700.23   201.2  695.43
   206.2   693.9   216.2  694.18   225.8  696.86   235.7  697.61   255.3  697.74
   284.8  698.68   314.2  699.27     324  699.65   333.9  700.34   343.7  701.44
   353.5   703.1   363.3  705.14   373.1   707.6   402.6  716.53   422.2  721.62
#Mann= 3 , 0 , 0
       0     .06       0   201.2    .045       0   216.2     .08       0
Bank Sta=201.2,216.2
XS Rating Curve= 0 ,0
Exp/Cntr=0.3,0.1

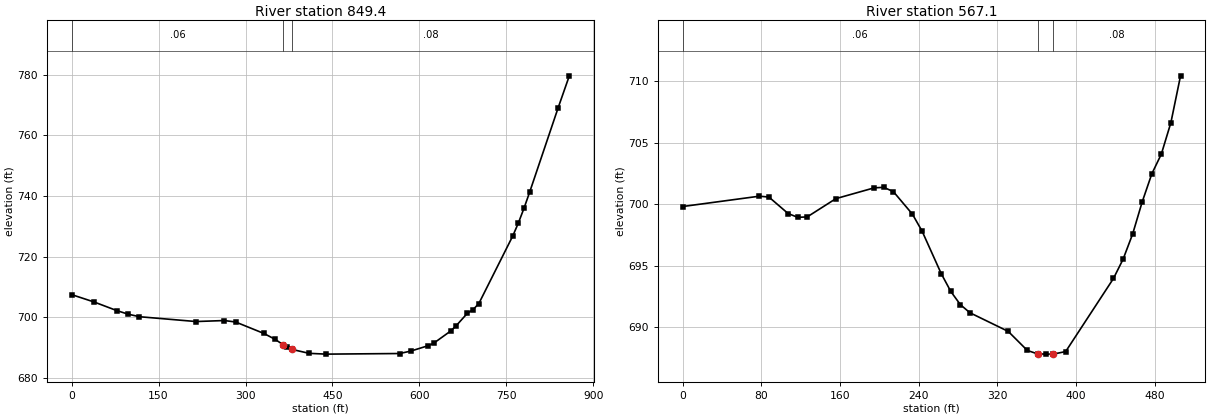
Type RM Length L Ch R = 1 ,849.4   ,277.7,282.4,204.1
XS GIS Cut Line= 2
      1472533.38      256943.446     1471675.358      256969.712
#Sta/Elev= 30
       0  707.44      39  704.99      78  702.16    97.6  700.98   117.1  700.14
   214.6  698.55   263.4  698.88   282.9   698.4   331.7  694.62   351.2  692.66
   364.9   690.9   370.7  690.16   380.4  689.34   409.7  688.06     439   687.8
   565.8     688   585.3  688.82   614.6  690.56   624.3  691.37   653.6   695.4
   663.3  697.17   682.8  701.32   692.6  702.51   702.4   704.5   760.9  726.79
   770.6  731.09   780.4     736   790.1  741.29   838.9  768.93   858.4   779.6
#Mann= 3 , 0 , 0
       0     .06       0   364.9    .045       0   380.4     .08       0
Bank Sta=364.9,380.4
XS Rating Curve= 0 ,0
Exp/Cntr=0.3,0.1

Type RM Length L Ch R = 1 ,567.1   ,547.5,567.1,585
XS GIS Cut Line= 2
     1472318.619      256827.266     1471813.511      256859.997
#Sta/Elev= 30
       0  699.82    77.9  700.66    87.6  700.59   107.1  699.25   116.8  698.94
   126.5  698.97   155.7  700.46   194.7  701.34   204.4  701.38   214.2  701.03
   233.6  699.19   243.4  697.81   262.8  694.36   272.6   692.9   282.3  691.83
     292  691.17     331  689.65   350.4   688.1   360.8  687.82   369.9   687.8
   376.7   687.8   389.4  688.01     438  693.96   447.8  695.53   457.5  697.58
   467.2  700.19     477  702.48   486.7  704.09   496.4  706.65   506.2  710.46
#Mann= 3 , 0 , 0
       0     .06       0   360.8    .045       0   376.7     .08       0
Bank Sta=360.8,376.7
XS Rating Curve= 0 ,0
Exp/Cntr=0.3,0.1

Chan Stop Cuts=-1
Use User Specified Reach Order=0
Composite Channel Slope=5